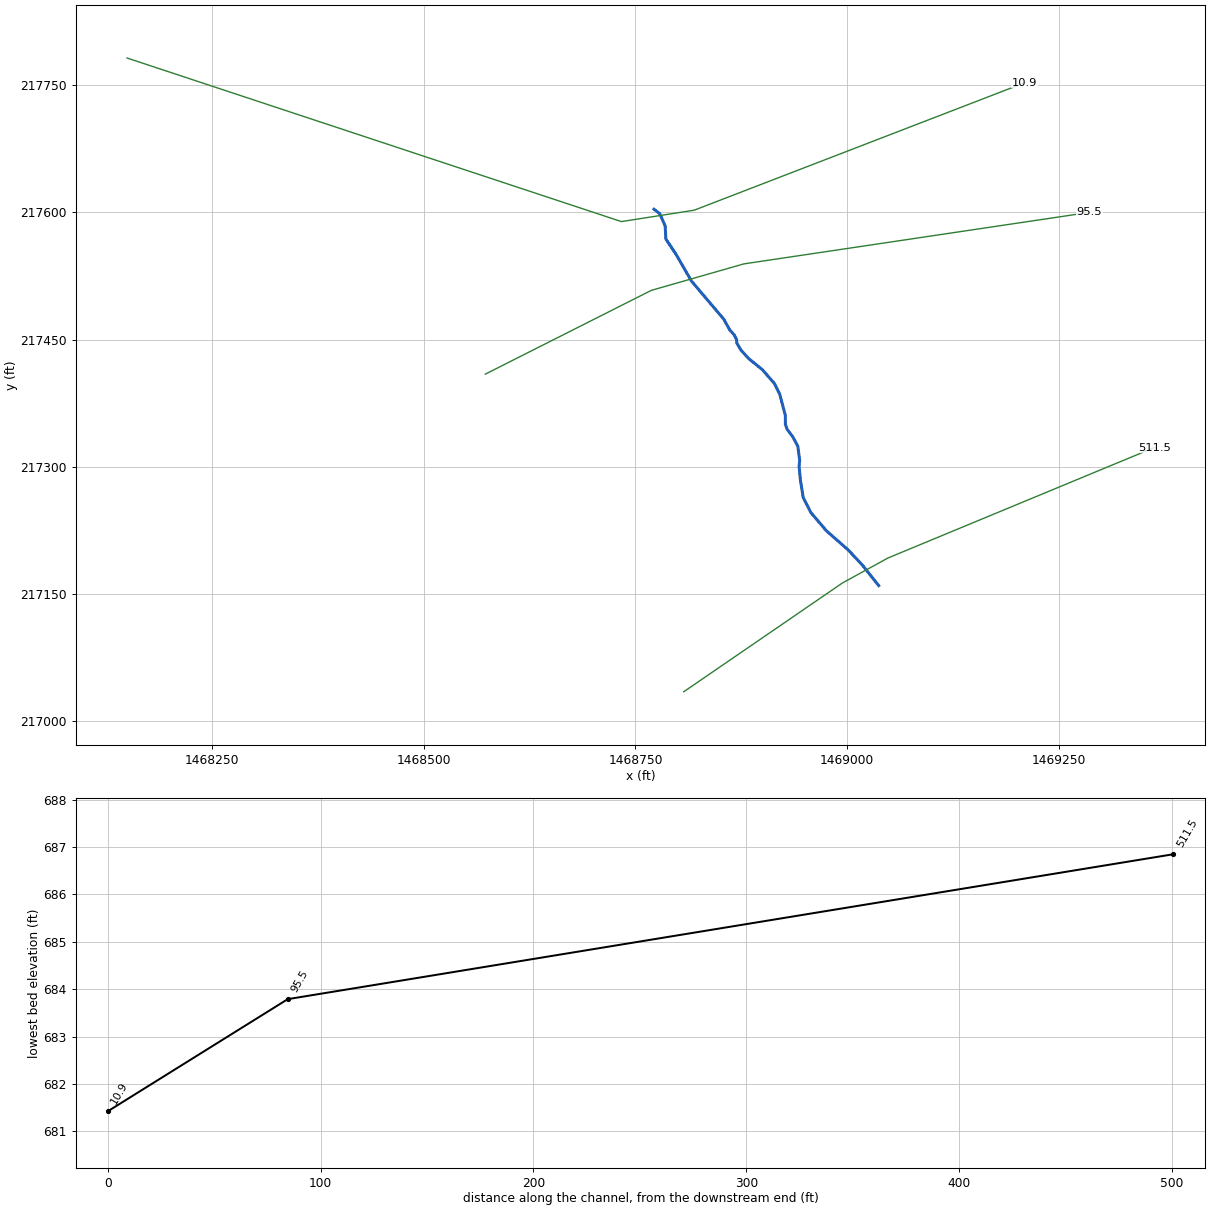
--- DRFTFR.prj (project) ---

Proj Title=DRFTFR
Current Plan=p01
Default Exp/Contr=0,0
English Units
Geom File=g01
Flow File=f01
Plan File=p01
BEGIN DESCRIPTION:
END DESCRIPTION:
DSS Export Rating Curves= 0
DSS Export Rating Curve Sorted= 0
DSS Export Volume Flow Curves= 0
DXF OffsetX= 0
DXF OffsetY= 0
DXF ScaleX= 0
DXF ScaleY= 0

--- DRFTFR.p01 (plan) ---

Plan Title=Floodplain
Program Version=4.00
Geom File=g01
Flow File=f01
K Sum by GR=0
Std Step Tol=0.01
Critical Tol=0.01
Num of Std Step Trials=20
Max Error Tol=0.3
Flow Tol Ratio=0.001
Split Flow NTrial=30
Split Flow Tol=0.02
Split Flow Ratio=0.02
Log Output Level=0
Friction Slope Method=1
Unsteady Friction Slope Method=2
Unsteady Bridges Friction Slope Method=1
Global Log Level=0
CheckData=False
Run HTab=0
Run UNet=0
Run PostProcess=0
UNET Theta=0
UNET Theta Warmup=0
UNET ZTol=0
UNET ZSATol=0
UNET MxIter=0
UNET MaxInSteps=0
UNET DtIC=0
UNET DtMin=0
UNET MaxCRTS=0
UNET WFStab=0
UNET SFStab=0
UNET WFX=0
UNET SFX=0
UNET DSS MLevel=0
UNET DZMax Abort=0
UNET Convert EG Bridges=0
UNET Use Existing IB Tables=0
UNET Froude Limit=0
UNET Froude Power=0
Write IC File=0
Echo Input=False
Echo Output=False
Write Detailed=0

--- DRFTFR.f01 (steady flow) ---

Flow Title=NFF Regression Equation
Program Version=4.10
Number of Profiles= 1
Profile Names=P100yr
River Rch & RM=DRFTFR,Main            ,511.5
 888.693
River Rch & RM=DRFTFR,Main            ,95.5
891.6087
Boundary for River Rch & Prof#=DRFTFR,Main            , 1
Up Type= 0
Dn Type= 1
Dn Known WS=686.46
DSS Import GetInterval= 0
DSS Import GetPeak= 0
DSS Import FillOption= 0

--- DRFTFR.g01 (geometry) ---

Geom Title=USGS 10m DEM
Program Version=4.10

River Reach=DRFTFR          ,Main
Reach XY= 30
     1469037.344       217159.43      1469017.75      217184.056
     1469001.084      217201.765     1468975.563      217224.161
     1468957.334      217245.515     1468948.175      217263.392
     1468944.834      217284.057     1468943.271      217300.202
     1468943.968        217307.4     1468941.776      217323.992
     1468935.719      217335.359     1468929.209      217343.952
     1468927.125      217349.681     1468927.021      217360.619
     1468920.354      217385.619     1468914.104      217398.119
     1468900.042      217414.265     1468883.375      217427.807
     1468874.521      217437.702     1468869.834      217445.515
     1468869.313      217450.202     1468866.709      217455.411
       1468861.5       217461.14     1468854.209       217474.16
     1468816.188      217518.952     1468798.089      217550.376
     1468785.936      217568.605     1468785.068       217584.23
     1468778.734      217598.492     1468771.911      217603.857

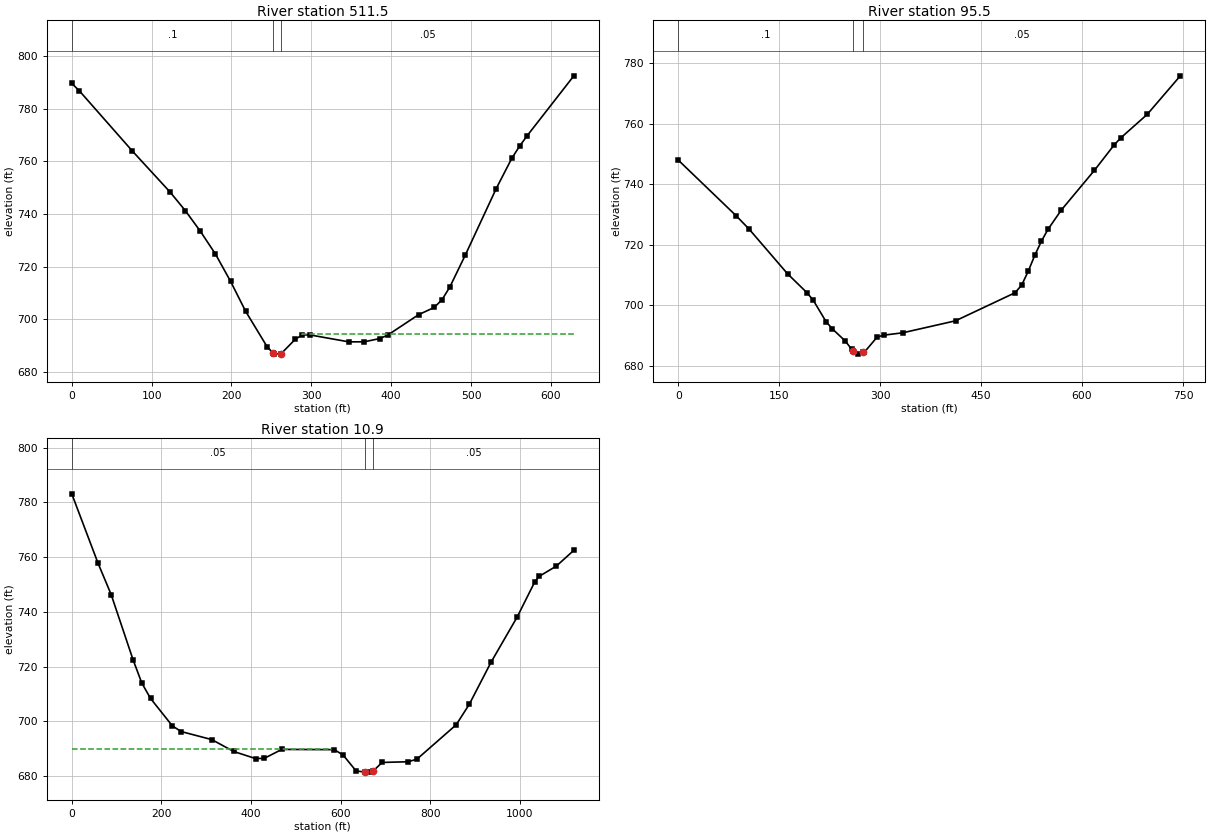
Type RM Length L Ch R = 1 ,511.5   ,418.9,416,408.2
XS GIS Cut Line= 4
      1468807.01      217034.114      1468994.51      217162.586
     1469048.329        217192.1     1469362.565      217322.309
#Sta/Elev= 30
       0  789.66     9.5  786.83    75.8     764   123.1   748.4   142.1  741.38
     161  733.52   179.9  724.88   198.9  714.47   217.8  703.08   244.8  689.58
   251.7  687.44   253.6  686.85   262.4  687.08   279.9  692.48   288.7  694.15
   298.4  694.14     347  691.51   366.4  691.53   385.9  692.78   395.6  694.05
   434.4  701.84   453.9  704.57   463.6  707.47   473.3  712.23   492.8  724.42
   531.6  749.73   551.1  761.21   560.8   765.8   570.5  769.85   628.8  792.53
#Mann= 3 , 0 , 0
       0      .1       0   251.7    .045       0   262.4     .05       0
#XS Ineff= 2 , 0
                           288.5          694.33
Permanent Ineff=
       F       F
Bank Sta=251.7,262.4
XS Rating Curve= 0 ,0
Exp/Cntr=0.3,0.1

Type RM Length L Ch R = 1 ,95.5    ,90.4,84.6,82
XS GIS Cut Line= 4
     1468572.635      217409.114     1468768.815      217508.073
      1468878.19      217539.323     1469286.176      217600.086
#Sta/Elev= 30
       0  747.96      86  729.56   105.1  725.18   162.4  710.36   191.1  704.14
   200.6  701.61   219.7  694.51   229.2  692.09   248.2  688.13   257.6  685.41
   260.1  684.98   267.1  683.79   275.1  684.35   276.6  684.45   295.6  689.44
     305  690.05   333.5  690.84     412  694.81   500.4  704.08   510.3  706.62
   520.1  711.24   529.9  716.53   539.7  721.18   549.5  725.09   569.2  731.44
   618.3  744.54   647.8  752.99   657.6  755.31   696.9  763.09     746  775.82
#Mann= 3 , 0 , 0
       0      .1       0   260.1    .045       0   275.1     .05       0
Bank Sta=260.1,275.1
XS Rating Curve= 0 ,0
Exp/Cntr=0.3,0.1

Type RM Length L Ch R = 1 ,10.9    ,0,10.9,28.1
XS GIS Cut Line= 4
     1468149.458      217782.378     1468733.399      217589.244
     1468819.423      217602.699     1469209.397      217753.003
#Sta/Elev= 30
       0  783.08    58.6  757.73    87.9  746.28   136.7  722.48   156.2  713.98
   175.7  708.34   224.5   698.3   244.1  696.24   312.4   693.3   361.2  688.97
     410  686.37   429.6  686.47   468.6  689.72   585.8  689.63   605.3  687.67
   634.4  681.84   653.8  681.46   663.4  681.42   673.1  681.93   692.4  684.96
   750.7  685.21   770.2  686.18   857.6  698.71   886.8  706.19   935.4  721.58
   993.7  738.09  1032.6  750.82  1042.3  752.89  1081.2   756.7  1120.1  762.45
#Mann= 3 , 0 , 0
       0     .05       0   653.8    .045       0   673.1     .05       0
#XS Ineff= 2 , 0
          577.93   689.8
Permanent Ineff=
       F       F
Bank Sta=653.8,673.1
XS Rating Curve= 0 ,0
Exp/Cntr=0.3,0.1

Chan Stop Cuts=-1
Use User Specified Reach Order=0
Composite Channel Slope=5